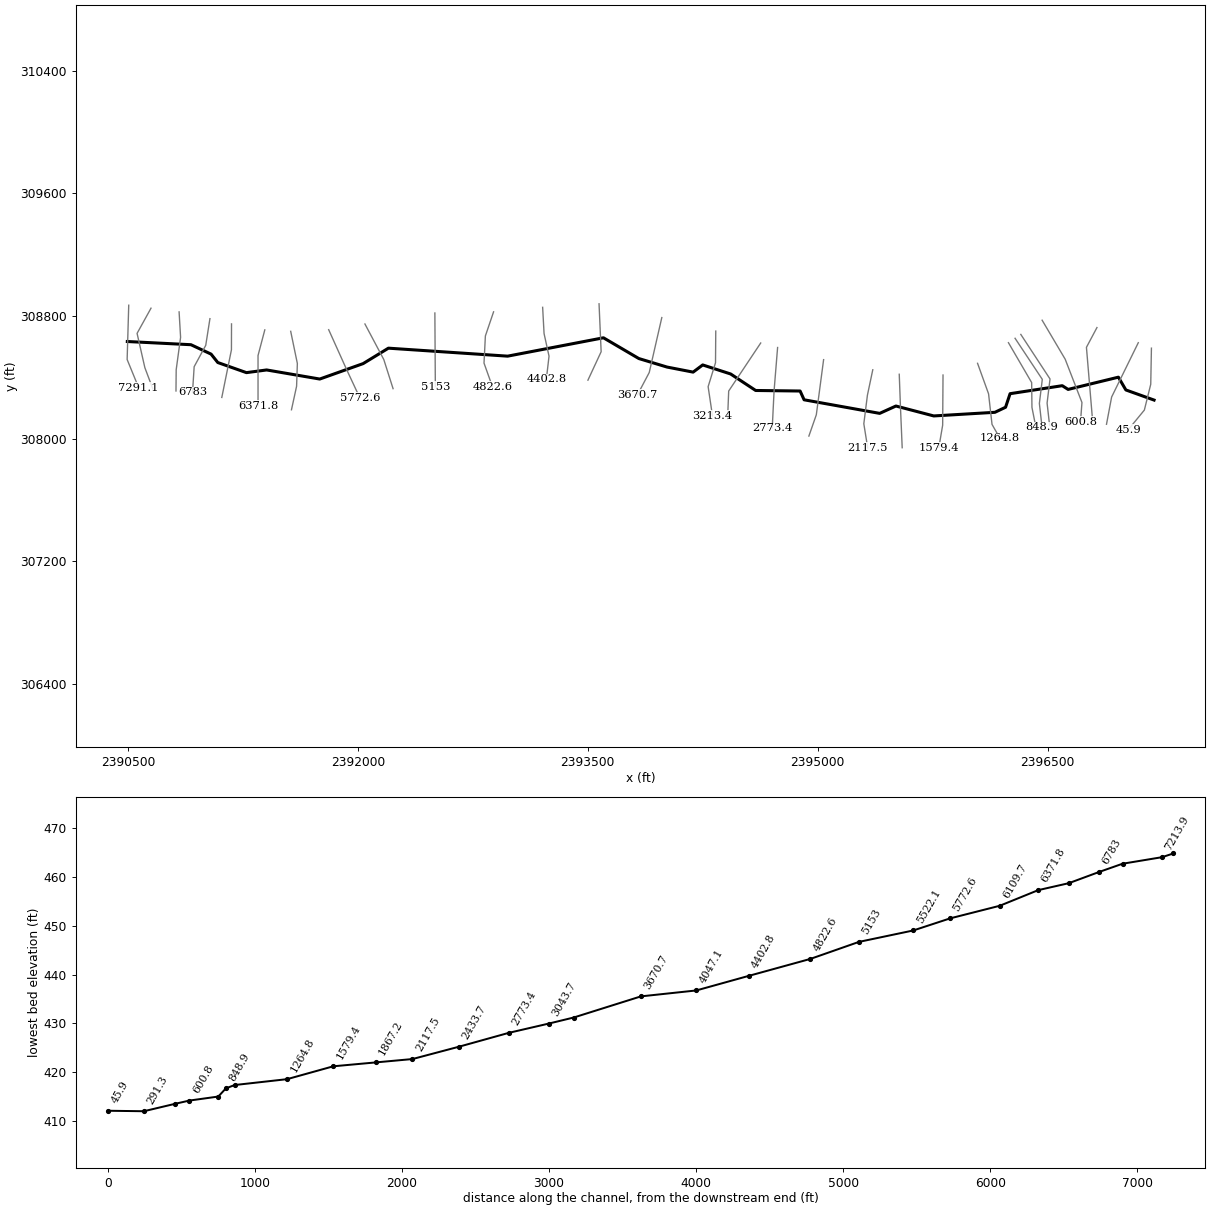
--- THREERUN.prj (project) ---

Proj Title=THREERUN
Current Plan=p01
Default Exp/Contr=0,0
English Units
Geom File=g01
Flow File=f01
Plan File=p01
BEGIN DESCRIPTION:
END DESCRIPTION:
DSS Export Rating Curves= 0
DSS Export Rating Curve Sorted= 0
DSS Export Volume Flow Curves= 0
DXF OffsetX= 0
DXF OffsetY= 0
DXF ScaleX= 0
DXF ScaleY= 0

--- THREERUN.p01 (plan) ---

Plan Title=Floodplain
Program Version=4.00
Geom File=g01
Flow File=f01
K Sum by GR=0
Std Step Tol=0.01
Critical Tol=0.01
Num of Std Step Trials=20
Max Error Tol=0.3
Flow Tol Ratio=0.001
Split Flow NTrial=30
Split Flow Tol=0.02
Split Flow Ratio=0.02
Log Output Level=0
Friction Slope Method=1
Unsteady Friction Slope Method=2
Unsteady Bridges Friction Slope Method=1
Global Log Level=0
CheckData=False
Run HTab=0
Run UNet=0
Run PostProcess=0
UNET Theta=0
UNET Theta Warmup=0
UNET ZTol=0
UNET ZSATol=0
UNET MxIter=0
UNET MaxInSteps=0
UNET DtIC=0
UNET DtMin=0
UNET MaxCRTS=0
UNET WFStab=0
UNET SFStab=0
UNET WFX=0
UNET SFX=0
UNET DSS MLevel=0
UNET DZMax Abort=0
UNET Convert EG Bridges=0
UNET Use Existing IB Tables=0
UNET Froude Limit=0
UNET Froude Power=0
Write IC File=0
Echo Input=False
Echo Output=False
Write Detailed=0

--- THREERUN.f01 (steady flow) ---

Flow Title=NFF Regression Equation
Program Version=4.10
Number of Profiles= 1
Profile Names=P100yr
River Rch & RM=THREERUN,Main            ,7291.1
485.9231
River Rch & RM=THREERUN,Main            ,7213.9
486.1844
River Rch & RM=THREERUN,Main            ,6783
587.4329
River Rch & RM=THREERUN,Main            ,6579.7
591.5632
River Rch & RM=THREERUN,Main            ,3213.4
736.7396
River Rch & RM=THREERUN,Main            ,3213.4
653.7837
River Rch & RM=THREERUN,Main            ,505.5
774.4814
River Rch & RM=THREERUN,Main            ,291.3
1039.599
Boundary for River Rch & Prof#=THREERUN,Main            , 1
Up Type= 0
Dn Type= 3
Dn Slope=0.0032
DSS Import GetInterval= 0
DSS Import GetPeak= 0
DSS Import FillOption= 0

--- THREERUN.g01 (geometry) ---

Geom Title=USGS 10m DEM
Program Version=4.10

River Reach=THREERUN        ,Main
Reach XY= 30
     2390496.337      308633.778     2390911.267      308612.945
     2391042.725      308551.556     2391086.475      308496.695
     2391273.219      308430.778     2391405.055      308448.248
     2391751.545      308388.987     2392034.531      308489.681
     2392199.462      308590.376     2392977.239      308538.292
     2393602.239      308658.084     2393833.142      308522.667
      2394017.17      308467.112     2394187.309      308434.126
     2394249.809      308481.001       2394432.1      308421.973
     2394595.295      308314.334     2394885.226      308310.862
     2394911.267       308253.57     2395404.323      308165.029
     2395510.206      308213.012     2395757.081      308148.255
     2396156.059      308171.973     2396225.503      308204.959
     2396255.017      308293.501     2396595.295      308345.584
     2396633.489      308321.279     2396961.614       308401.14
     2397010.226      308317.806     2397194.253      308251.834

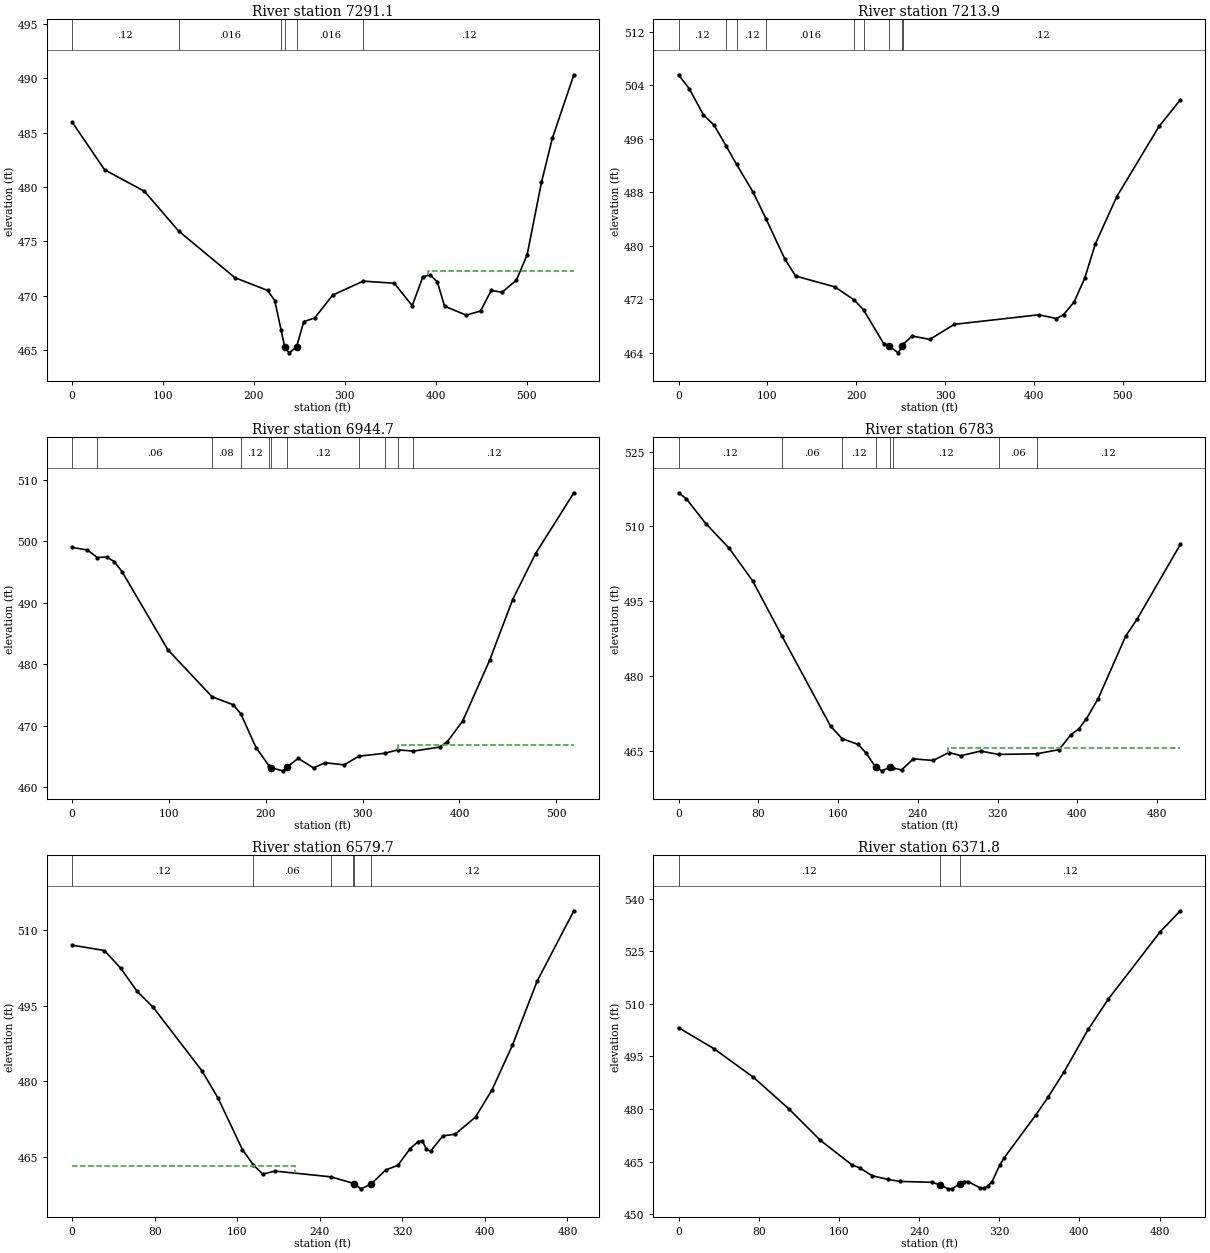
Type RM Length L Ch R = 1 ,7291.1  ,71.2,77.2,83.2
XS GIS Cut Line= 3
      2390505.48      308870.614     2390495.083      308516.339
     2390569.997      308333.518
#Sta/Elev= 30
       0  485.97    35.8  481.57    79.6   479.6  117.24475.9391   179.2  471.65
     215  470.48     223  469.54   229.9  466.85  233.96465.2566   238.9  464.74
   246.9  465.28   254.9  467.61   266.8  467.94   286.7  470.05  320.28471.3336
   354.4  471.14   374.2  469.08     386  471.75   393.9   471.9   401.8  471.27
   409.8  469.03   433.5  468.21   449.3  468.58   461.1  470.48     473  470.31
   488.8  471.42   500.6  473.76   516.4  480.43   528.3  484.46     552  490.31
#Mann= 6 ,-1 , 0
       0     .12       0  117.24    .016       0   229.9    .045       0
  233.96    .045       0   246.9    .016       0  320.28     .12       0
#XS Ineff= 2 , 0
                          391.95           472.3
Permanent Ineff=
       F       F
Bank Sta=233.96,246.9
XS Rating Curve= 0 ,0
Exp/Cntr=0.3,0.1

Type RM Length L Ch R = 1 ,7213.9  ,277.2,269.1,261
XS GIS Cut Line= 4
      2390650.86      308851.306     2390559.927      308686.999
     2390610.708      308463.041     2390662.618      308325.012
#Sta/Elev= 30
       0  505.54      12  503.47      28  499.56      40  498.01   53.62494.8987
   65.31492.1463    83.9  488.01   98.84483.9121   119.9  477.93   131.8  475.45
   175.8  473.84  197.72471.8776  208.29470.4013   231.3  465.27  236.53465.0613
   247.2  463.97  252.07 465.011   252.8  465.23     263  466.48   282.8  465.98
   310.5  468.23   405.6  469.66   425.4   469.1   433.4  469.67   445.3  471.56
   457.3  475.13   469.2  480.24   493.2  487.29     541  497.84   564.9  501.79
#Mann= 9 ,-1 , 0
       0     .12       0   53.62     .06       0   65.31     .12       0
   98.84    .016       0  197.72     .12       0  208.29    .016       0
  236.53    .045       0  252.07    .045       0   252.8     .12       0
Bank Sta=236.53,252.07
XS Rating Curve= 0 ,0
Exp/Cntr=0.3,0.1

Type RM Length L Ch R = 1 ,6944.7  ,169.8,161.7,153.5
XS GIS Cut Line= 4
     2390834.086      308826.971     2390843.781      308660.958
     2390815.046      308449.501     2390813.714      308311.136
#Sta/Elev= 30
       0  498.97    15.8  498.55    26.1497.3239    35.6  497.42    43.6  496.66
    51.5  495.05      99  482.31  144.49474.6857   166.3  473.38  174.12471.9412
     190   466.4   203.6  463.39   205.8  463.12   217.7  462.63   221.6  463.19
   233.5  464.66   249.3   463.1   261.1  463.95   280.9   463.6  296.09465.0037
  322.73465.4899  336.41466.0442  352.29465.8356   379.7   466.5   387.6   467.4
   403.4  470.76   431.1   480.6   454.8  490.45   478.5  497.95   518.1  507.86
#Mann= 11 ,-1 , 0
       0     .08       0    26.1     .06       0  144.49     .08       0
  174.12     .12       0   203.6    .045       0   205.8    .045       0
   221.6     .12       0  296.09     .06       0  322.73     .12       0
  336.41     .06       0  352.29     .12       0
#XS Ineff= 2 , 0
                          336.22          466.84
Permanent Ineff=
       F       F
Bank Sta=205.8,221.6
XS Rating Curve= 0 ,0
Exp/Cntr=0.3,0.1

Type RM Length L Ch R = 1 ,6783    ,196.6,203.4,209.7
XS GIS Cut Line= 4
     2391035.213       308782.87     2391007.843      308608.874
     2390932.322      308469.551     2390921.513      308301.236
#Sta/Elev= 30
       0  516.74     7.8  515.53    27.4  510.54    50.9  505.58    74.4  499.03
   103.9487.9115   152.6  469.87  163.93467.4047   180.1  466.21     188  464.52
  197.86461.6202   203.9  460.92   211.8  461.62   215.2  461.49   223.7  461.11
   235.6  463.33   255.4     463   271.2   464.6   283.1  463.96   302.9  464.88
  321.09464.2171  359.08464.3392   381.7  465.17   393.4  468.16   401.3   469.3
   409.1  471.37   420.9  475.41   448.4  487.92   460.1  491.42   503.3  506.36
#Mann= 8 ,-1 , 0
       0     .12       0   103.9     .06       0  163.93     .12       0
  197.86    .045       0   211.8    .045       0   215.2     .12       0
  321.09     .06       0  359.08     .12       0
#XS Ineff= 2 , 0
                          270.59          465.47
Permanent Ineff=
       F       F
Bank Sta=197.86,211.8
XS Rating Curve= 0 ,0
Exp/Cntr=0.3,0.1

Type RM Length L Ch R = 1 ,6579.7  ,203.3,207.8,212.3
XS GIS Cut Line= 3
     2391175.993      308748.775     2391175.465      308579.794
      2391112.63      308268.884
#Sta/Elev= 30
       0  507.01    31.4  505.93    47.2   502.4    62.9  497.87    78.6  494.67
   125.8  482.08   141.5  476.64     165  466.46  175.74463.3736   184.8  461.59
   196.7  462.18  250.72461.0428   272.6  459.75  273.42459.5908     280  458.66
   289.5 459.568   303.8  462.39   315.7  463.33   327.6  466.65   335.5  468.05
   339.5  468.14   343.4  466.52   347.4  466.13   359.3  469.17   371.2  469.49
     391  472.92   406.9   478.3   426.7  487.16   450.5  499.81   486.2  513.82
#Mann= 6 ,-1 , 0
       0     .12       0  175.74     .06       0  250.72     .12       0
   272.6    .045       0  273.42    .045       0   289.5     .12       0
#XS Ineff= 2 , 0
           216.2  463.24
Permanent Ineff=
       F       F
Bank Sta=273.42,289.5
XS Rating Curve= 0 ,0
Exp/Cntr=0.3,0.1

Type RM Length L Ch R = 1 ,6371.8  ,262.6,262.2,261.4
XS GIS Cut Line= 3
     2391393.152      308709.709     2391348.989      308542.468
     2391348.989      308214.764
#Sta/Elev= 30
       0  503.22    35.4  497.21    74.7  489.08   110.1  480.06   141.5  471.09
     173  464.08     181   463.2     193     461   208.9  459.92   220.9  459.36
   252.9   459.1   260.9  458.38   268.9  457.24   272.9  457.29   280.9  458.63
   284.9  459.28   288.9  459.31   300.9  457.51   304.9  457.46   308.8  458.08
   312.8  459.27   320.8  464.17   324.8  466.02   356.8  478.43   368.8  483.44
   384.8  490.68   408.8  502.74   428.7  511.32   480.7  530.61   500.7  536.57
#Mann= 3 ,-1 , 0
       0     .12       0   260.9    .045       0   280.9     .12       0
Bank Sta=260.9,280.9
XS Rating Curve= 0 ,0
Exp/Cntr=0.3,0.1

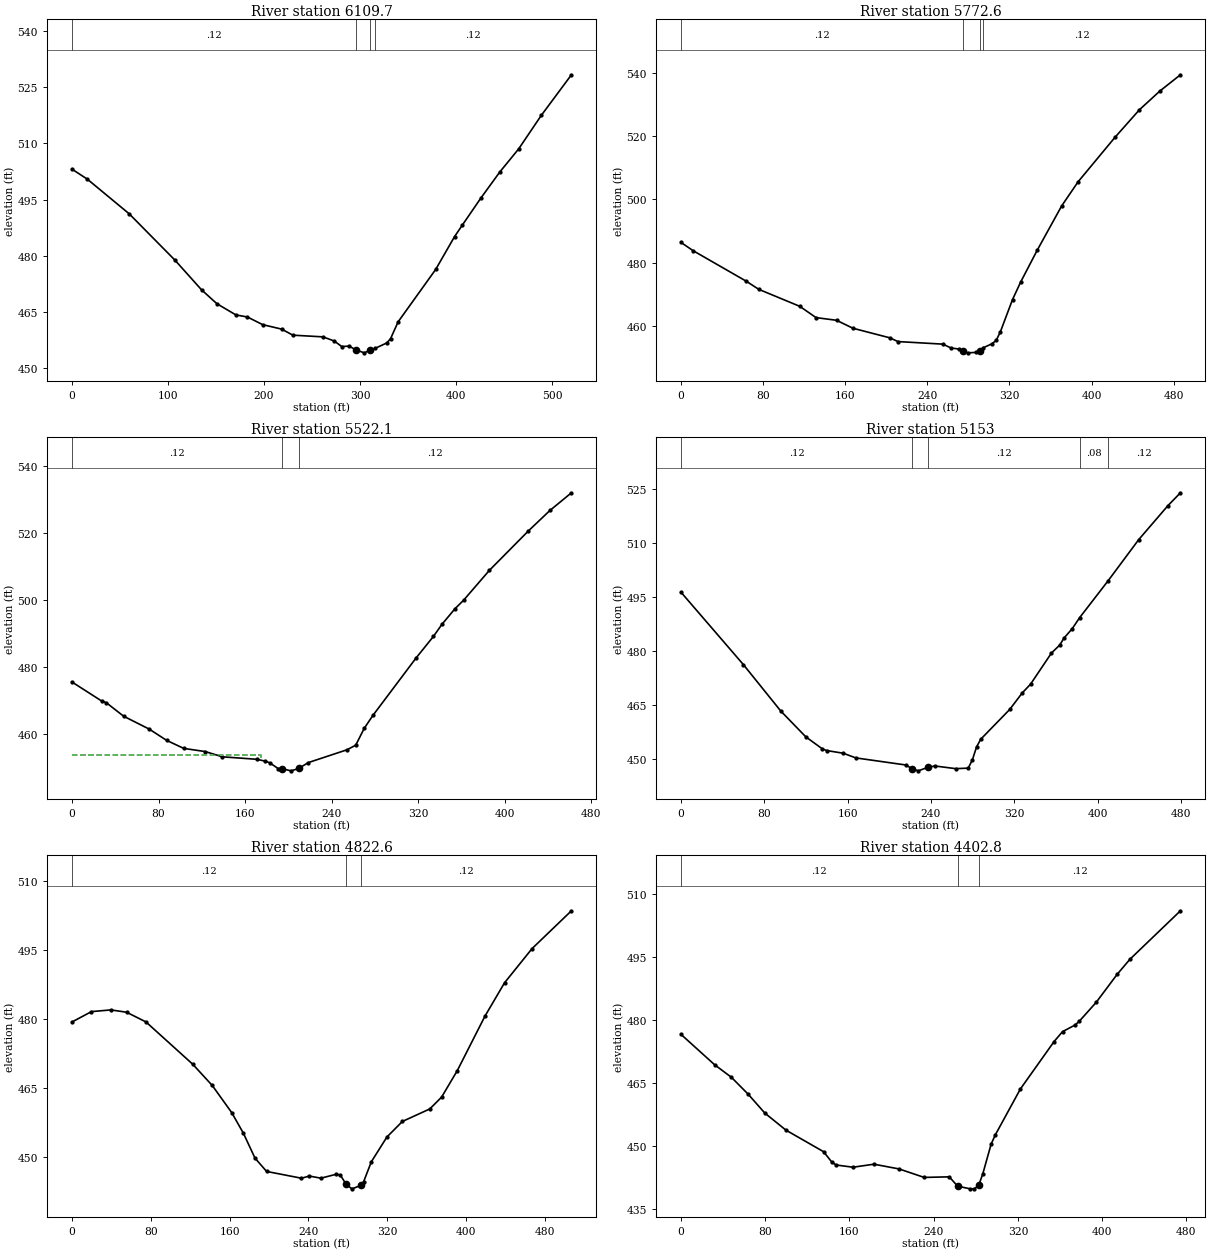
Type RM Length L Ch R = 1 ,6109.7  ,326.8,337.1,347.8
XS GIS Cut Line= 4
     2391562.035      308700.326     2391605.499      308490.385
     2391600.472      308341.853     2391567.105      308188.435
#Sta/Elev= 30
       0  503.14    15.9  500.48    59.6   491.2   107.2  478.82     135  470.86
   150.9  467.17   170.7  464.17   182.6  463.63   198.5  461.58   218.3  460.38
     230  458.76   261.3  458.31   273.1   457.2   280.9  455.72   288.7  455.84
  295.54454.8217   304.4  454.04   310.4454.7677   315.5  455.22   327.8  456.69
   331.7  457.82   339.5   462.3   378.7  476.34   398.3   485.1   406.2   488.1
   425.8  495.44   445.4  502.37   465.1  508.56   488.6   517.5     520  528.36
#Mann= 4 ,-1 , 0
       0     .12       0  295.54    .045       0   310.4    .045       0
   315.5     .12       0
Bank Sta=295.54,310.4
XS Rating Curve= 0 ,0
Exp/Cntr=0.3,0.1

Type RM Length L Ch R = 1 ,5772.6  ,248.8,250.4,251.7
XS GIS Cut Line= 3
     2391809.877       308710.87     2391927.713      308449.012
      2392012.24      308268.333
#Sta/Elev= 30
       0  486.35      12  483.71    63.8  474.06    75.8  471.53   115.7  466.17
   131.6   462.6   151.6  461.75   167.5  459.24   203.4  456.22   211.4  455.03
   255.2  454.22   263.2  452.98   271.2  452.67   275.2   452.1   279.2  451.47
   287.2   451.6   291.1  452.06   294.6  453.09   303.1  454.35   307.1  455.42
   311.1  458.04     323   468.3     331  473.87     347  483.85   370.9  497.89
   386.9  505.51   422.8  519.54   446.7  528.28   466.7  534.21   486.6  539.31
#Mann= 4 ,-1 , 0
       0     .12       0   275.2    .045       0   291.1    .045       0
   294.6     .12       0
Bank Sta=275.2,291.1
XS Rating Curve= 0 ,0
Exp/Cntr=0.3,0.1

Type RM Length L Ch R = 1 ,5522.1  ,380.1,369.2,358.2
XS GIS Cut Line= 3
     2392046.338      308748.073     2392169.302      308516.426
     2392229.859      308326.401
#Sta/Elev= 30
       0  475.56    27.8   469.8    31.8  469.36    47.7  465.34    71.5  461.46
    87.4  458.13   103.3  455.71   123.2  454.76   139.1  453.19   170.9  452.45
   178.8  451.89   182.8   451.4   190.7  449.66   194.5  449.58   202.7     449
   209.5  449.71   218.6  451.48   254.3   455.3   262.3  456.67   270.2  461.72
   278.2  465.57   318.1  482.74   334.1  489.16     342  492.79     354  497.43
     362  499.99   385.9  508.94   421.8  520.67   441.8  526.82   461.7  532.11
#Mann= 3 ,-1 , 0
       0     .12       0   194.5    .045       0   209.5     .12       0
#XS Ineff= 2 , 0
          174.92  453.68
Permanent Ineff=
       F       F
Bank Sta=194.5,209.5
XS Rating Curve= 0 ,0
Exp/Cntr=0.3,0.1

Type RM Length L Ch R = 1 ,5153    ,331.7,330.4,329.1
XS GIS Cut Line= 2
      2392502.57      308819.838     2392505.649      308340.262
#Sta/Elev= 30
       0  496.32      60  476.17    95.9  463.27   119.9  456.11   135.9  452.75
   139.9  452.31   155.9  451.56   167.8  450.27   215.8   448.3   222.3  447.19
   227.8  446.67   237.3  447.66   243.8  448.02   263.8  447.28   275.8  447.42
   279.8   449.7   283.8  453.29   287.8  455.44   315.7  463.74   327.7  468.32
   335.7  470.76   355.7  479.38   363.7  481.63   367.7  483.53   375.7  486.18
  382.73489.2102  409.89499.3902   439.6  510.95   467.6  520.37   479.6  523.94
#Mann= 5 ,-1 , 0
       0     .12       0   222.3    .045       0   237.3     .12       0
  382.73     .08       0  409.89     .12       0
Bank Sta=222.3,237.3
XS Rating Curve= 0 ,0
Exp/Cntr=0.3,0.1

Type RM Length L Ch R = 1 ,4822.6  ,413.7,419.8,425.9
XS GIS Cut Line= 4
     2392885.523      308827.311     2392832.062      308670.072
     2392823.135      308493.089     2392878.144      308338.869
#Sta/Elev= 30
       0  479.34    19.8  481.59    39.5  481.96    55.4  481.46    75.1  479.36
   122.6  470.19   142.4  465.59   162.1  459.73     174  455.25   185.8  449.84
   197.6  446.96     233  445.49   240.9  445.96   252.7   445.5   268.5  446.36
   272.4  446.18   278.4  444.14   284.2  443.19   293.4  443.93     296   444.7
   303.9  449.06   319.7  454.42   335.4  457.79   363.2   460.5   375.2  463.06
   391.2  468.83   419.2   480.6   439.1  487.84   467.1  495.26     507  503.44
#Mann= 3 ,-1 , 0
       0     .12       0   278.4    .045       0   293.4     .12       0
Bank Sta=278.4,293.4
XS Rating Curve= 0 ,0
Exp/Cntr=0.3,0.1

Type RM Length L Ch R = 1 ,4402.8  ,359.3,355.7,351.5
XS GIS Cut Line= 4
     2393205.603      308856.859     2393214.874      308685.697
     2393247.248      308538.237     2393229.758      308387.281
#Sta/Elev= 30
       0  476.53    31.9   469.3    47.8  466.32    63.8  462.28    79.7  457.76
    99.7  453.71   135.5  448.56   143.5  446.02   147.5   445.4   163.4  444.87
   183.3  445.59   207.2  444.46     231  442.44   254.8  442.58   262.8  440.36
   274.7  439.72   278.7  439.73   282.7  440.52   286.6  443.22   294.6  450.38
   298.6  452.59   322.4  463.52   354.4  474.82   362.4  477.17   374.4  478.76
   378.4  479.67   394.4  484.16   414.4  490.86   426.4  494.41   474.4  505.97
#Mann= 3 ,-1 , 0
       0     .12       0   262.8    .045       0   282.7     .12       0
Bank Sta=262.8,282.7
XS Rating Curve= 0 ,0
Exp/Cntr=0.3,0.1

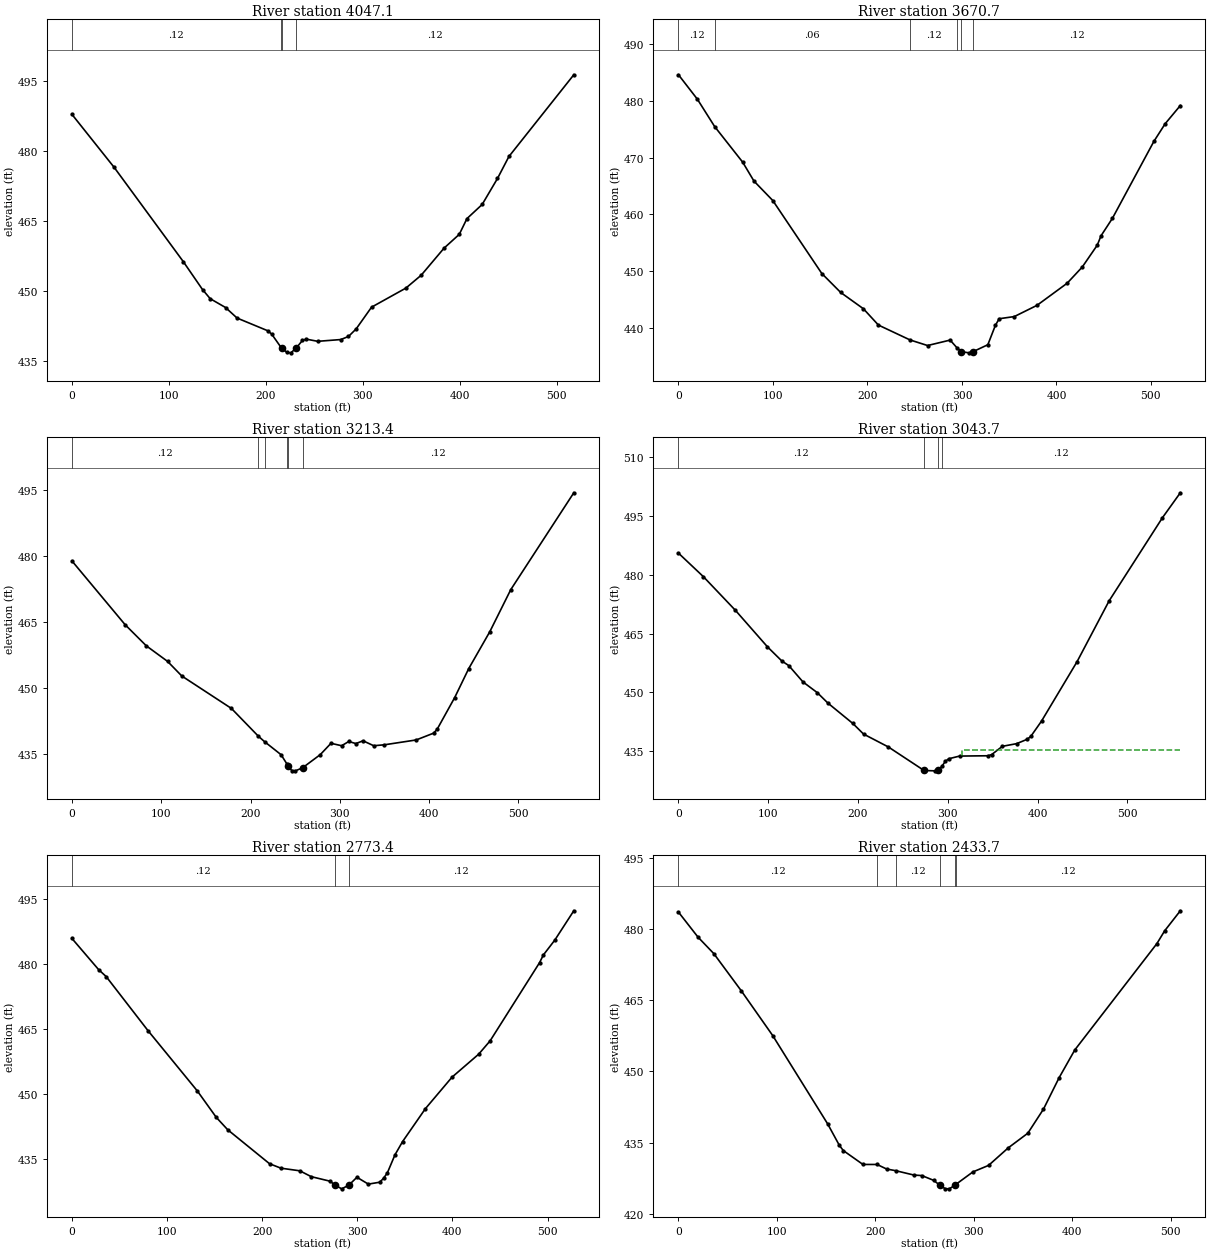
Type RM Length L Ch R = 1 ,4047.1  ,382.7,376.4,370.1
XS GIS Cut Line= 3
     2393573.565      308879.854      2393587.27      308567.208
     2393501.054      308381.623
#Sta/Elev= 30
       0  487.88    43.6   476.5   114.9  456.29   134.7  450.31   142.6  448.36
   158.4  446.47   170.3  444.21     202  441.48     206  440.77   215.5  437.96
  216.39437.7338   221.8  436.83   225.8  436.75  231.25437.7697   237.7   439.4
   241.6  439.69   253.5  439.22   277.3   439.6   285.2  440.26   293.1  441.87
     309  446.54   344.4  450.63   360.2  453.39   383.8   459.2   399.5  462.16
   407.4  465.53   423.1  468.56   438.9  474.14   450.7  478.85   517.6  496.37
#Mann= 4 ,-1 , 0
       0     .12       0   215.5    .045       0  216.39    .045       0
  231.25     .12       0
Bank Sta=216.39,231.25
XS Rating Curve= 0 ,0
Exp/Cntr=0.3,0.1

Type RM Length L Ch R = 1 ,3670.7  ,460.1,457.3,445.9
XS GIS Cut Line= 3
     2393982.983      308789.911     2393901.072      308431.791
     2393824.723      308286.991
#Sta/Elev= 30
       0  484.61      20   480.3    38.3 475.468    67.9   469.2    79.9  465.85
    99.8  462.42   151.7  449.54   171.7  446.19   195.7  443.32   211.6  440.44
  245.09437.8134   263.6  436.83   287.5  437.79   295.1  436.36   299.5  435.74
   307.5  435.54   311.5  435.73   327.4  436.97   335.4   440.4   339.4  441.56
   355.4  441.94   379.4  443.92   411.3  447.82   427.3  450.68   443.2  454.54
   447.2   456.2   459.2  459.27   503.1  472.85   515.1  475.98   531.1  479.18
#Mann= 6 ,-1 , 0
       0     .12       0    38.3     .06       0  245.09     .12       0
   295.1    .045       0   299.5    .045       0   311.5     .12       0
Bank Sta=299.5,311.5
XS Rating Curve= 0 ,0
Exp/Cntr=0.3,0.1

Type RM Length L Ch R = 1 ,3213.4  ,176.1,169.8,163
XS GIS Cut Line= 4
     2394334.951      308701.919     2394333.364      308495.593
     2394285.187      308339.343     2394313.445       308149.31
#Sta/Elev= 30
       0  478.86    59.5   464.4    83.3  459.59   107.1  456.06     123  452.75
   178.6  445.38   208.8  439.07  215.72 437.838   234.2  434.88     241  432.69
   242.2  432.21   246.2  431.28   250.2  431.22   258.2   431.9   278.1   434.9
   290.1  437.47     302  436.92     310  437.88     318  437.41     326  438.04
   337.9  436.92   349.9  437.13   385.5  438.23   405.1  439.78     409  440.67
   428.6  447.84   444.3  454.41   467.9  462.78   491.4  472.34     562  494.33
#Mann= 6 ,-1 , 0
       0     .12       0   208.8     .06       0  215.72     .12       0
     241    .045       0   242.2    .045       0   258.2     .12       0
Bank Sta=242.2,258.2
XS Rating Curve= 0 ,0
Exp/Cntr=0.3,0.1

Type RM Length L Ch R = 1 ,3043.7  ,259.1,270.2,282.1
XS GIS Cut Line= 3
     2394628.151      308624.015     2394419.302      308310.697
     2394412.044      308128.531
#Sta/Elev= 30
       0  485.56    27.8  479.54    63.4  470.96    99.1  461.64     115  458.05
   122.9  456.84   138.7  452.67   154.6  449.94   166.5  447.26   194.2  442.07
   206.1  439.37   233.8  436.07   273.5  430.07   285.4  429.98   289.4  430.15
   293.5  431.18   297.3  432.44   301.2  433.08   313.1  433.75   344.8  433.83
   348.8  434.13   360.7  436.24   376.6  436.92   388.4  438.04   392.4  438.78
   404.3  442.67   443.9  457.85   479.6  473.38     539  494.61   558.9  500.97
#Mann= 4 ,-1 , 0
       0     .12       0   273.5    .045       0   289.4    .045       0
   293.5     .12       0
#XS Ineff= 2 , 0
                          315.79           435.2
Permanent Ineff=
       F       F
Bank Sta=273.5,289.4
XS Rating Curve= 0 ,0
Exp/Cntr=0.3,0.1

Type RM Length L Ch R = 1 ,2773.4  ,341.1,339.7,336.3
XS GIS Cut Line= 3
     2394738.351      308594.684     2394715.366      308312.034
     2394703.377      308068.354
#Sta/Elev= 30
       0  485.89      28  478.71      36  477.09    79.9  464.63   131.8   450.7
   151.8  444.58   163.8  441.73   207.7   433.9   219.7  432.87   239.6  432.26
   251.6  430.91   271.6  429.85   276.1  429.02   283.6   428.1   291.1  428.95
   299.6  430.77   311.6  429.19   323.6  429.63   327.6  430.54   331.6  431.79
   339.6  435.95   347.6  439.01   371.6  446.61   399.6  453.88   427.6  459.18
   439.6  462.25   491.6   480.3   495.6  482.08   507.6   485.5   527.6  492.28
#Mann= 3 ,-1 , 0
       0     .12       0   276.1    .045       0   291.1     .12       0
Bank Sta=276.1,291.1
XS Rating Curve= 0 ,0
Exp/Cntr=0.3,0.1

Type RM Length L Ch R = 1 ,2433.7  ,316.1,316.3,316.2
XS GIS Cut Line= 3
     2395038.504      308515.512     2394990.916      308155.749
     2394942.467      308017.038
#Sta/Elev= 30
       0   483.6    19.9  478.31    35.9  474.85    63.8  467.01    95.7  457.58
   151.5  438.97   163.5   434.4   167.5  433.32   187.4   430.4  201.76430.3964
   211.4  429.44  220.58429.0916   239.3  428.16   247.2  428.06   259.2  427.05
  265.83425.9698   271.2  425.26   275.2  425.28  280.63425.9889   281.9  426.21
   299.1  428.83     315   430.2     335   433.9   354.9  436.99   370.8  442.07
   386.7   448.7   402.6  454.54     486  476.96   493.9  479.66   509.8  483.88
#Mann= 6 ,-1 , 0
       0     .12       0  201.76     .06       0  220.58     .12       0
  265.83    .045       0  280.63    .045       0   281.9     .12       0
Bank Sta=265.83,280.63
XS Rating Curve= 0 ,0
Exp/Cntr=0.3,0.1

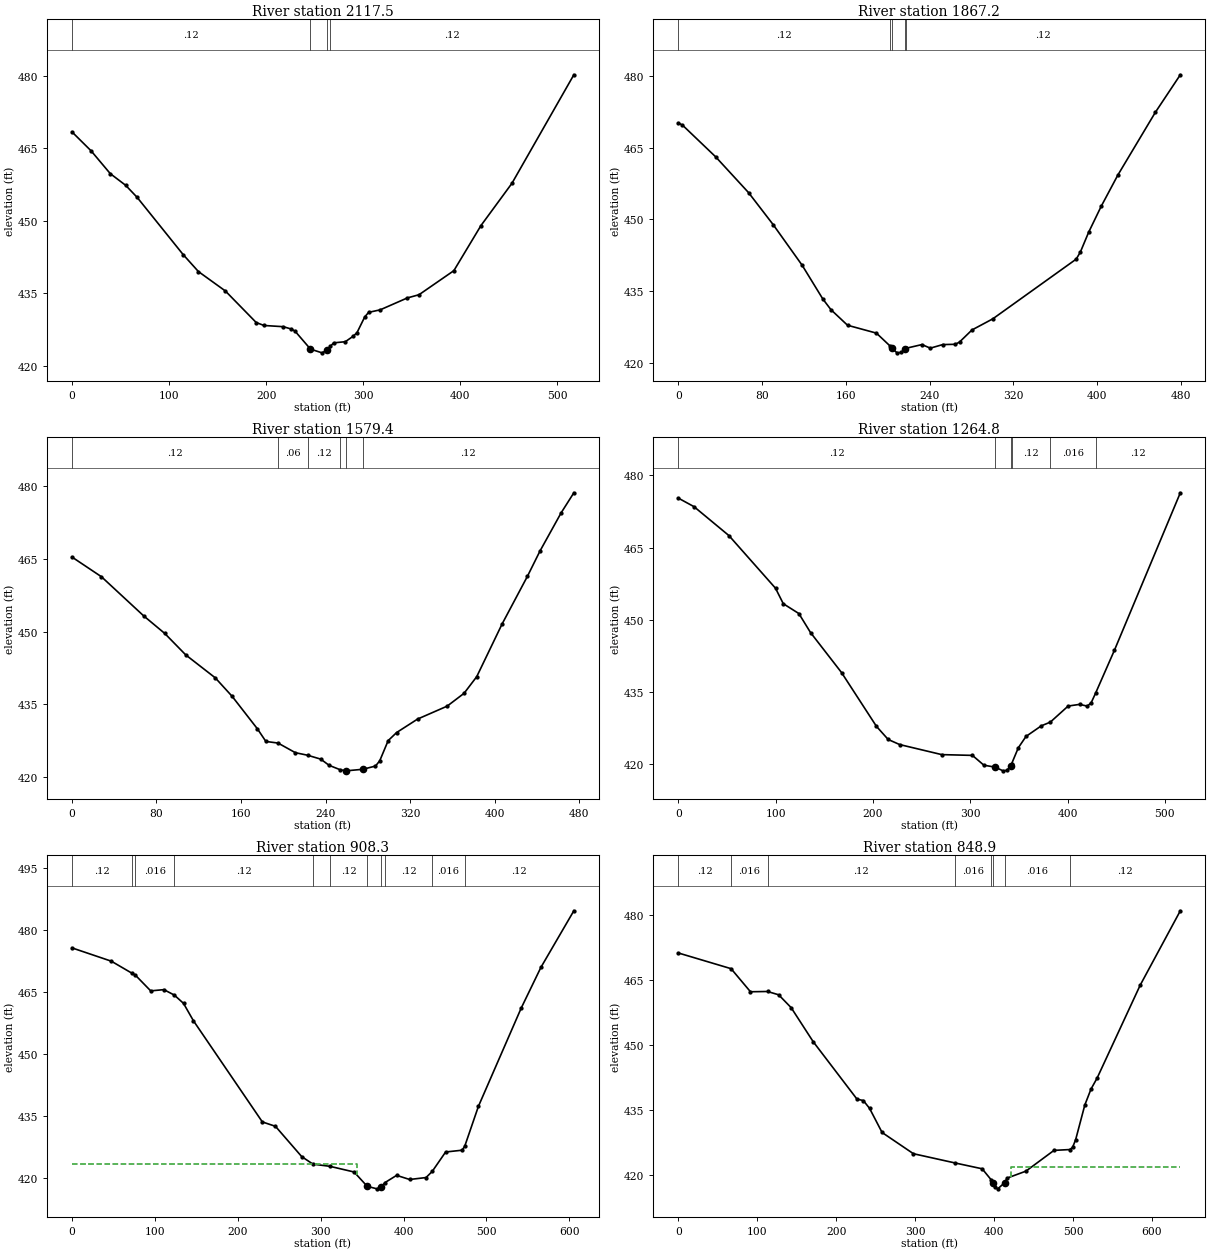
Type RM Length L Ch R = 1 ,2117.5  ,246.1,250.3,254.6
XS GIS Cut Line= 4
     2395359.264        308449.5     2395324.249      308283.353
     2395300.812      308097.155     2395326.136      307939.673
#Sta/Elev= 30
       0  468.37    19.7  464.46    39.5  459.74    55.3  457.34    67.1  454.86
   114.5  443.04   130.3  439.52     158  435.52   189.8     429   197.8  428.39
   217.7  428.14   225.7  427.67   229.7  427.24   245.7  423.51   257.6  422.74
  262.78423.2862     266  424.05   269.6   424.8   281.6  425.04   289.6  426.16
   293.6   426.9   301.6  430.16   305.6   431.1   317.5  431.62   345.5  434.08
   357.5  434.74   393.4  439.71   421.3  449.02   453.2  457.74     517  480.16
#Mann= 4 ,-1 , 0
       0     .12       0   245.7    .045       0  262.78    .045       0
     266     .12       0
Bank Sta=245.7,262.78
XS Rating Curve= 0 ,0
Exp/Cntr=0.3,0.1

Type RM Length L Ch R = 1 ,1867.2  ,288.3,287.8,286.1
XS GIS Cut Line= 3
     2395531.935      308420.221     2395539.813      308207.534
     2395551.125      307940.977
#Sta/Elev= 30
       0   470.2     3.9  469.75    35.5  463.13      67  455.62    90.6  448.89
   118.2  440.41     138  433.33   145.8  431.08   161.6  427.83   189.2  426.18
   202.4  423.45   204.1422.9923   208.9  422.05   212.8  422.13   216.8  422.92
   217.4     423   232.7  423.78   240.7  423.03   252.6  423.78   264.6  423.84
   268.6  424.31   280.5  426.84   300.4  429.17   380.1  441.68   384.1  443.17
     392  447.31     404  452.75   419.9  459.29   455.7  472.42   479.6   480.3
#Mann= 5 ,-1 , 0
       0     .12       0   202.4    .045       0   204.1    .045       0
   216.8    .045       0   217.4     .12       0
Bank Sta=204.1,216.8
XS Rating Curve= 0 ,0
Exp/Cntr=0.3,0.1

Type RM Length L Ch R = 1 ,1579.4  ,311.9,314.6,317.4
XS GIS Cut Line= 3
     2395817.482      308415.124     2395815.135      308088.041
     2395790.339      307942.364
#Sta/Elev= 30
       0  465.42    27.9  461.35    67.8  453.28    87.8  449.64   107.7   445.2
   135.6  440.47   151.6  436.64   175.5  429.93   183.5  427.33  194.99426.9968
   211.4  425.01   222.9 424.485   235.4  423.68   243.3   422.4     254  421.47
   259.3  421.26   275.2  421.58   287.2  422.25   291.2  423.32   299.2   427.5
   307.2  429.17   327.1  431.96     355  434.62     371  437.27     383  440.71
     407  451.59   430.9  461.41   442.9  466.68   462.9  474.56   474.9  478.69
#Mann= 6 ,-1 , 0
       0     .12       0  194.99     .06       0   222.9     .12       0
     254    .045       0   259.3    .045       0   275.2     .12       0
Bank Sta=259.3,275.2
XS Rating Curve= 0 ,0
Exp/Cntr=0.3,0.1

Type RM Length L Ch R = 1 ,1264.8  ,359.6,356.6,351.8
XS GIS Cut Line= 4
     2396042.758       308491.53     2396114.614      308292.468
     2396137.158      308093.001     2396188.461      308003.057
#Sta/Elev= 30
       0  475.28      16  473.52    51.9  467.51    99.8  456.57   107.8  453.35
   123.8  451.31   135.8  447.36   167.7  439.04   203.6  427.86   215.6  425.15
   227.4  424.09   270.7     422   302.2  421.84     314   419.8   325.8  419.39
   333.6  418.63   337.6  418.72   341.5  419.64   342.5   420.1   349.4  423.43
   357.3  425.78     373  427.98  382.27428.7491   400.6  432.09   412.4  432.44
   420.3  432.07   424.3  432.79  428.77434.7515   448.2   443.7   515.9   476.4
#Mann= 6 ,-1 , 0
       0     .12       0   325.8    .045       0   341.5    .045       0
   342.5     .12       0  382.27    .016       0  428.77     .12       0
Bank Sta=325.8,341.5
XS Rating Curve= 0 ,0
Exp/Cntr=0.3,0.1

Type RM Length L Ch R = 1 ,908.3   ,62.4,59.4,56.1
XS GIS Cut Line= 4
     2396244.283      308626.071      2396395.69      308365.992
       2396397.6      308204.274     2396425.335      308064.176
#Sta/Elev= 30
       0   475.7    47.5  472.48      72469.6154   76.46469.1184      95   465.3
   110.9   465.6  123.49464.2868   134.6  462.28   146.5  458.09   229.7  433.61
   245.5  432.55   277.2  425.22  290.82423.3977  311.14422.8783   340.4   421.5
   356.2  418.04     368  417.43   373.1 417.887   377.7  418.95   391.7  420.69
   407.4  419.69   427.2  420.16   434.7 421.659   450.8  426.34   470.6  426.77
  473.78427.6843   490.4   437.4     542  461.15   565.8     471   605.5  484.67
#Mann= 11 ,-1 , 0
       0     .12       0      72     .08       0   76.46    .016       0
  123.49     .12       0  290.82     .06       0  311.14     .12       0
   356.2    .045       0   373.1    .045       0   377.7     .12       0
   434.7    .016       0  473.78     .12       0
#XS Ineff= 2 , 0
          343.86  423.38
Permanent Ineff=
       F       F
Bank Sta=356.2,373.1
XS Rating Curve= 0 ,0
Exp/Cntr=0.3,0.1

Type RM Length L Ch R = 1 ,848.9   ,51.8,51.5,51.8
XS GIS Cut Line= 4
     2396287.436       308654.88     2396465.135      308386.826
     2396446.038      308229.708     2396463.426      308074.581
#Sta/Elev= 30
       0  471.21   66.75467.5881    91.3  462.26  112.94462.3231     127  461.56
   142.9  458.58   170.7  450.75   226.3  437.46   234.3  437.14   242.2  435.34
   258.1  429.76   297.8  424.86  350.24422.7377   384.9  421.38   396.7  418.75
  398.16418.1769   400.7  417.18   404.7  416.75  413.28 418.161   416.6  419.24
   440.3  420.83   475.9  425.63  495.81425.8213   499.4   426.3   503.3  428.06
     515  436.12   522.8  439.78   530.6  442.34   585.2   463.8     636  480.96
#Mann= 8 ,-1 , 0
       0     .12       0   66.75    .016       0  112.94     .12       0
  350.24    .016       0   396.7    .045       0  398.16    .045       0
  413.28    .016       0  495.81     .12       0
#XS Ineff= 2 , 0
                          421.16          421.89
Permanent Ineff=
       F       F
Bank Sta=398.16,413.28
XS Rating Curve= 0 ,0
Exp/Cntr=0.3,0.1

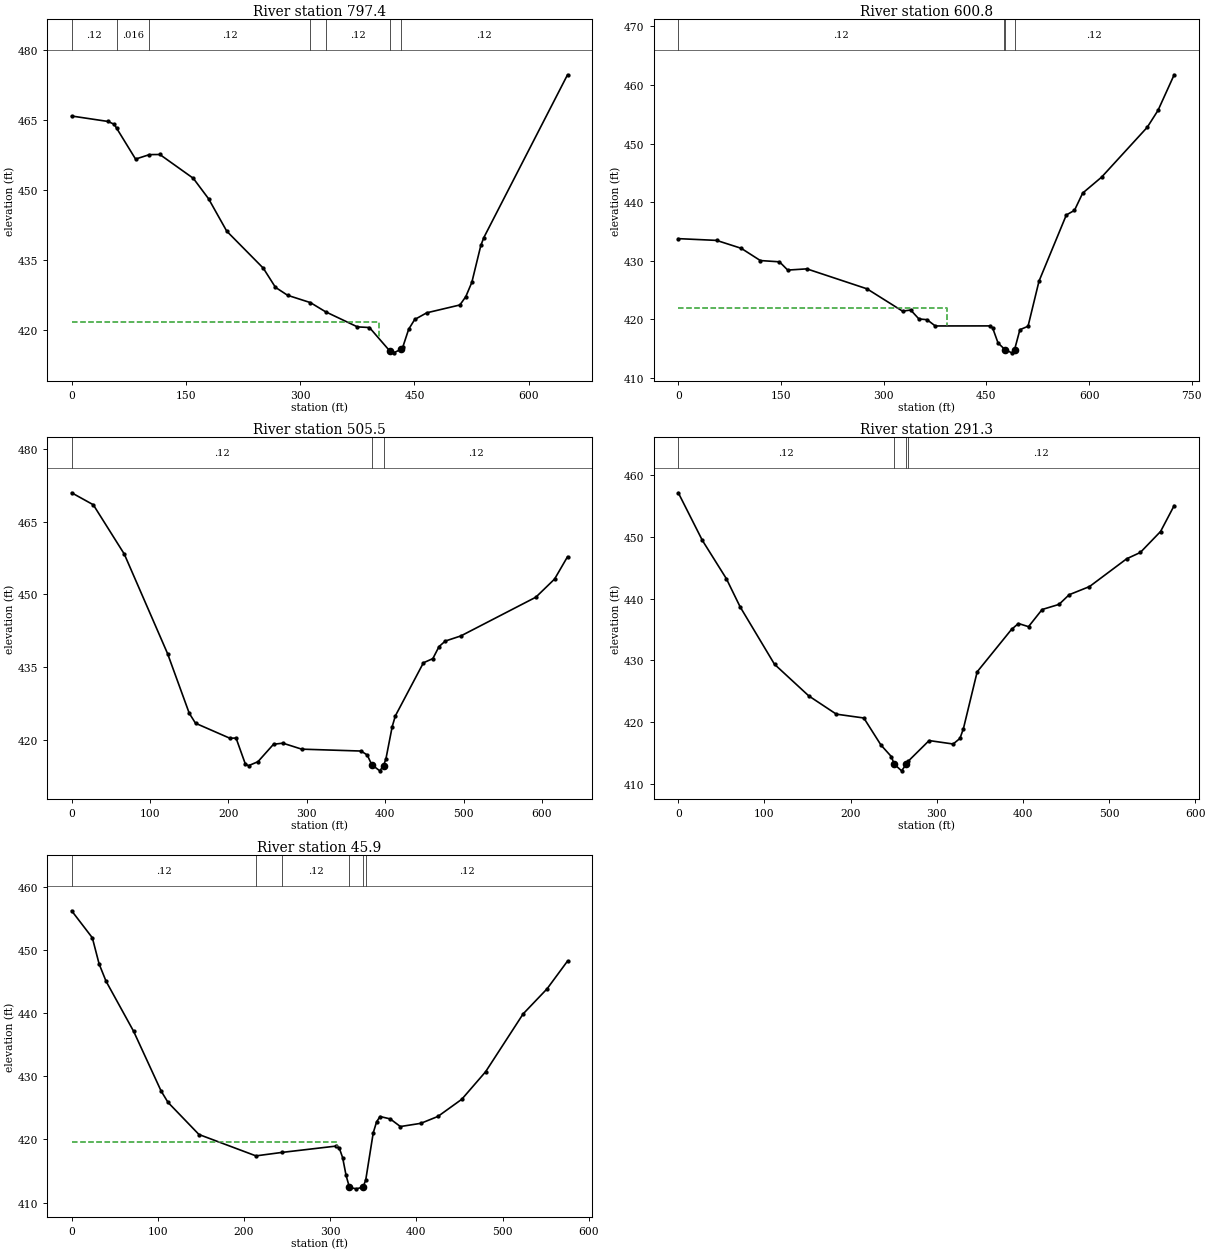
Type RM Length L Ch R = 1 ,797.4   ,183.4,196.6,208.7
XS GIS Cut Line= 4
     2396324.996      308679.956     2396515.482       308389.43
     2396496.385      308232.312     2396512.561      308088.003
#Sta/Elev= 30
       0  465.79    47.9  464.62    55.9  464.01   59.26463.1196    83.9  456.57
  102.19 457.526   115.8  457.55   159.7  452.45   179.7  448.08   203.6  441.13
   251.6   433.2   267.5  429.11   283.5   427.4  313.48425.8317  333.29423.8746
   375.1  420.64   390.9   420.5   417.6  415.48   422.6  415.08   432.6  415.85
   434.5  416.23   442.4  420.14   450.3  422.22   466.1  423.65   509.6  425.33
   517.4  427.12   525.3  430.18   537.1  438.07     541  439.75   650.9  474.62
#Mann= 7 ,-1 , 0
       0     .12       0   59.26    .016       0  102.19     .12       0
  313.48    .016       0  333.29     .12       0   417.6    .045       0
   432.6     .12       0
#XS Ineff= 2 , 0
          403.82  421.59
Permanent Ineff=
       F       F
Bank Sta=417.6,432.6
XS Rating Curve= 0 ,0
Exp/Cntr=0.3,0.1

Type RM Length L Ch R = 1 ,600.8   ,102.3,95.3,88.3
XS GIS Cut Line= 4
        2396464.      308772.757      2396614.44      308518.336
     2396723.815      308235.784     2396714.393      308110.521
#Sta/Elev= 30
       0  433.76    55.9  433.46    91.9  432.11   119.8  430.02   147.8   429.8
   159.8  428.39   187.7   428.6   275.6  425.19   327.5  421.38   339.4  421.57
   351.4  420.05   363.3  419.92   375.3  418.85     455  418.86     459  418.54
     467  415.94   475.7  414.97  477.65414.8045   486.9  414.26  491.12 414.811
   498.9  418.21   510.8   418.8   526.8   426.5   566.7   437.8   578.6  438.59
   590.6  441.54   618.2  444.26   684.9  452.78   700.6  455.66   724.2  461.74
#Mann= 4 ,-1 , 0
       0     .12       0   475.7    .045       0  477.65    .045       0
  491.12     .12       0
#XS Ineff= 2 , 0
          392.98  421.86
Permanent Ineff=
       F       F
Bank Sta=477.65,491.12
XS Rating Curve= 0 ,0
Exp/Cntr=0.3,0.1

Type RM Length L Ch R = 1 ,505.5   ,226.8,214.3,201.7
XS GIS Cut Line= 4
     2396821.645       308724.76     2396753.069      308595.853
     2396792.348       308127.51     2396790.332       308111.11
#Sta/Elev= 30
       0  470.92    27.6  468.45    67.1   458.3   122.3  437.79     150  425.48
     158  423.42   201.8  420.33   209.7  420.37   221.7  414.95   225.7  414.68
   237.6  415.49   257.5  419.09   269.5  419.31   293.4  418.08   369.1  417.69
     377  416.88   382.8  414.88     393  413.61   397.8  414.66   400.9   416.1
   408.9  422.74   412.9  424.94   448.7  435.88   460.7  436.74   468.6  439.22
   476.6  440.36   496.5  441.42   592.1   449.4     616  453.14   632.5  457.74
#Mann= 3 ,-1 , 0
       0     .12       0   382.8    .045       0   397.8     .12       0
Bank Sta=382.8,397.8
XS Rating Curve= 0 ,0
Exp/Cntr=0.3,0.1

Type RM Length L Ch R = 1 ,291.3   ,240.9,245.3,249.8
XS GIS Cut Line= 3
     2397091.351      308626.058     2396917.348      308271.607
     2396883.929      308093.917
#Sta/Elev= 30
       0  457.17    27.9  449.46    55.8  443.24    71.8  438.67   111.7  429.36
   151.6  424.22   183.5  421.27   215.4  420.65   235.3  416.26   247.3   414.4
  250.64413.1809   259.2  412.08  264.74413.1452   266.7  413.61   291.2  416.99
   319.1  416.43     327  417.34     331  418.91     347  428.14   386.9  435.02
   394.9  435.97   406.6  435.46   422.4  438.24     442  439.07   453.8  440.64
   477.4  441.96   520.6  446.47   536.4  447.49   559.9  450.89   575.7  455.09
#Mann= 4 ,-1 , 0
       0     .12       0  250.64    .045       0  264.74    .045       0
   266.7     .12       0
Bank Sta=250.64,264.74
XS Rating Curve= 0 ,0
Exp/Cntr=0.3,0.1

Type RM Length L Ch R = 1 ,45.9    ,44.4,45.9,47.5
XS GIS Cut Line= 4
     2397177.028      308590.448     2397172.557      308354.941
      2397130.89      308186.538     2397025.427      308057.981
#Sta/Elev= 30
       0  456.24      24  451.96    31.9   447.8    39.9  445.08    71.9  437.14
   103.8  427.68   111.8  425.88   147.7  420.79  213.79417.4034  244.46417.9597
   306.5  418.95   310.5  418.64   314.4  417.12   318.4   414.3   322.3  412.41
   330.2  412.18   338.1  412.46   341.2  413.59   349.9  421.06   353.8   422.8
   357.8  423.64   369.6  423.26   381.4  422.05   405.1  422.56   424.9  423.65
   452.6  426.37   480.3  430.74   523.8   439.9   551.6  443.88   575.3  448.27
#Mann= 6 ,-1 , 0
       0     .12       0  213.79     .06       0  244.46     .12       0
   322.3    .045       0   338.1    .045       0   341.2     .12       0
#XS Ineff= 2 , 0
          308.36  419.54
Permanent Ineff=
       F       F
Bank Sta=322.3,338.1
XS Rating Curve= 0 ,0
Exp/Cntr=0.3,0.1

Chan Stop Cuts=-1
Use User Specified Reach Order=0
Composite Channel Slope=5